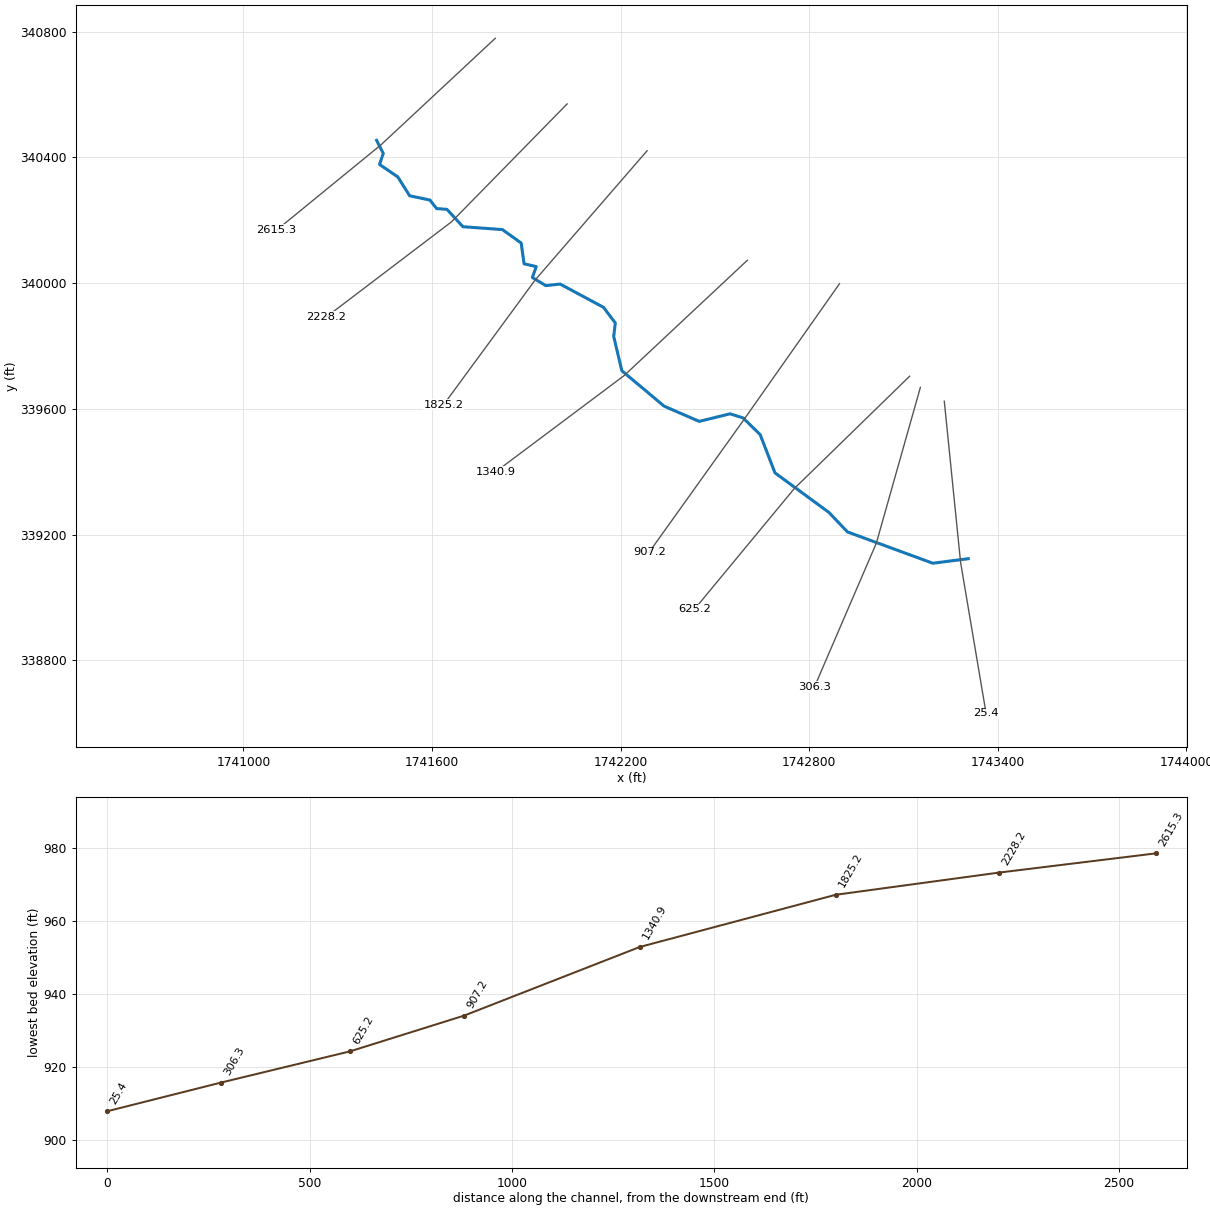
--- LongRn.prj (project) ---

Proj Title=LongRn
Current Plan=p01
Default Exp/Contr=0,0
English Units
Geom File=g01
Flow File=f01
Plan File=p01
BEGIN DESCRIPTION:
END DESCRIPTION:
DSS Export Rating Curves= 0
DSS Export Rating Curve Sorted= 0
DSS Export Volume Flow Curves= 0
DXF OffsetX= 0
DXF OffsetY= 0
DXF ScaleX= 0
DXF ScaleY= 0

--- LongRn.p01 (plan) ---

Plan Title=Floodplain
Program Version=4.00
Geom File=g01
Flow File=f01
K Sum by GR=0
Std Step Tol=0.01
Critical Tol=0.01
Num of Std Step Trials=20
Max Error Tol=0.3
Flow Tol Ratio=0.001
Split Flow NTrial=30
Split Flow Tol=0.02
Split Flow Ratio=0.02
Log Output Level=0
Friction Slope Method=1
Unsteady Friction Slope Method=2
Unsteady Bridges Friction Slope Method=1
Global Log Level=0
CheckData=False
Run HTab=0
Run UNet=0
Run PostProcess=0
UNET Theta=0
UNET Theta Warmup=0
UNET ZTol=0
UNET ZSATol=0
UNET MxIter=0
UNET MaxInSteps=0
UNET DtIC=0
UNET DtMin=0
UNET MaxCRTS=0
UNET WFStab=0
UNET SFStab=0
UNET WFX=0
UNET SFX=0
UNET DSS MLevel=0
UNET DZMax Abort=0
UNET Convert EG Bridges=0
UNET Use Existing IB Tables=0
UNET Froude Limit=0
UNET Froude Power=0
Write IC File=0
Echo Input=False
Echo Output=False
Write Detailed=0

--- LongRn.f01 (steady flow) ---

Flow Title=NFF Regression Equation
Program Version=4.00
Number of Profiles= 1
Profile Names=P100yr
River Rch & RM=LongRn,Main            ,2615.3
     722
River Rch & RM=LongRn,Main            ,306.3
784.4978
River Rch & RM=LongRn,Main            ,25.4
788.5428
Boundary for River Rch & Prof#=LongRn,Main            , 1
Up Type= 0
Dn Type= 3
Dn Slope=0.0298
DSS Import GetInterval= 0
DSS Import GetPeak= 0
DSS Import FillOption= 0

--- LongRn.g01 (geometry) ---

Geom Title=USGS 3m DEM
Program Version=4.00

River Reach=LongRn     ,Main
Reach XY= 30
     1741423.937      340454.066     1741445.131      340412.645
     1741433.194      340377.452     1741491.242      340337.876
     1741529.330      340277.596     1741593.635      340264.166
     1741614.738      340237.070     1741647.798      340234.513
     1741698.579      340179.365     1741824.002      340170.216
     1741883.889      340127.407     1741893.079      340061.323
     1741931.843      340052.513     1741919.549      340017.656
     1741962.128      339991.926     1742007.828      339996.966
     1742145.983      339922.686     1742183.363      339872.982
     1742178.232      339830.321     1742204.105      339721.170
     1742338.665      339608.449     1742450.221      339560.003
     1742548.387      339584.159     1742589.902      339571.015
     1742644.254      339517.841     1742691.329      339396.217
     1742862.755      339270.513     1742922.072      339208.239
     1743193.466      339108.746     1743306.076      339123.177

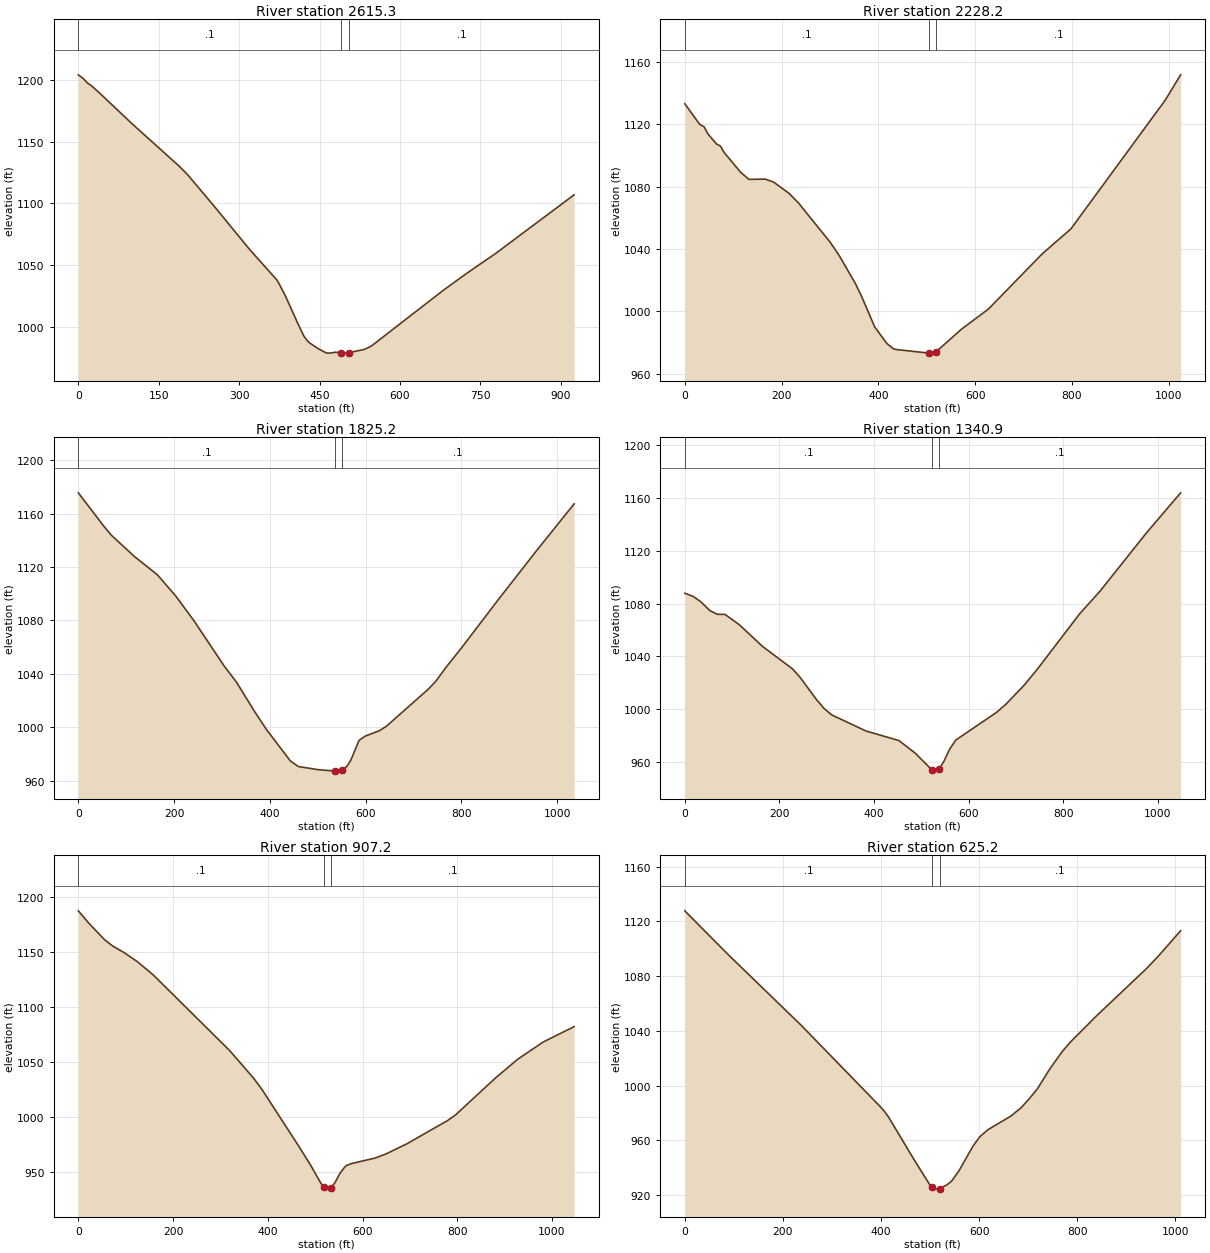
Type RM Length L Ch R = 1 ,2615.3,374.052,387.178,394.664
XS GIS Cut Line= 3
     1741801.322      340778.657     1741438.207      340440.128
     1741106.045      340168.717
#Sta/Elev= 30
       0 1204.09     8.8 1201.25    17.3 1197.35    25.1 1195.03    41.3 1188.66
   101.3 1164.01   187.4 1130.40   203.6 1123.32   252.8 1097.99   319.7 1062.55
   370.2 1038.02   374.7 1034.75   387.0 1024.38   409.5 1002.62   420.6  992.57
   426.9  988.77   430.9  987.08   447.1  982.33   463.3  978.60   471.0  978.68
   479.1  979.32   489.9  978.95   495.8  978.61   504.9  979.00   534.1  981.68
   546.8  984.37   679.8 1029.12   725.8 1043.61   778.0 1059.16   925.1 1106.89
#Mann= 3 , 0 , 0
       0     0.1       0   489.9   0.045       0   504.9     0.1       0
Bank Sta=   489.9,   504.9
Exp/Cntr=0.3,0.1

Type RM Length L Ch R = 1 ,2228.2,399.909,402.957,377.451
XS GIS Cut Line= 3
     1742030.078      340569.972     1741662.730      340195.221
     1741264.639      339892.750
#Sta/Elev= 30
       0 1133.07    30.7 1119.93    39.9 1118.35    47.7 1113.79    65.5 1107.32
    73.5 1106.02    81.6 1101.75   115.4 1089.20   132.5 1084.64   166.4 1084.81
   183.4 1082.92   215.2 1075.75   234.3 1069.78   300.2 1044.48   319.1 1035.86
   353.0 1017.65   364.8 1010.10   392.5  990.11   417.7  979.46   431.3  976.08
   437.8  975.60     505  973.34   505.6  973.33     520  974.37   571.4  988.58
   627.2 1001.49   738.7 1036.94   798.0 1052.95   992.9 1135.39  1024.7 1151.62
#Mann= 3 , 0 , 0
       0     0.1       0     505   0.045       0     520     0.1       0
Bank Sta=     505,     520
Exp/Cntr=0.3,0.1

Type RM Length L Ch R = 1 ,1825.2,485.9,484.331,478.785
XS GIS Cut Line= 3
     1742284.425      340420.957     1741929.049      340010.680
     1741637.260      339613.257
#Sta/Elev= 30
       0 1175.48    53.3 1150.50    69.0 1143.75   116.1 1128.18   165.2 1114.13
   203.7 1098.18   241.8 1079.65   304.6 1045.95   330.7 1033.66   366.9 1012.58
   392.4  998.73   442.9  974.88   459.8  970.67   501.9  968.30   535.3  967.35
   540.2  967.25   550.3  968.19   560.9  970.73   569.4  975.56   586.4  990.27
   599.3  993.44   628.7  997.47   643.5 1000.81   730.8 1028.47   746.6 1034.40
   769.5 1045.58   798.8 1058.69   879.1 1096.39   960.2 1133.54  1035.8 1167.23
#Mann= 3 , 0 , 0
       0     0.1       0   535.3   0.045       0   550.3     0.1       0
Bank Sta=   535.3,   550.3
Exp/Cntr=0.3,0.1

Type RM Length L Ch R = 1 ,1340.9,429.012,433.71,440.08
XS GIS Cut Line= 3
     1742603.403      340072.559     1742211.213      339705.512
     1741802.248      339399.181
#Sta/Elev= 30
       0 1087.85    17.9 1085.42    34.2 1081.29    52.9 1074.73    68.4 1071.94
    85.2 1071.77   115.5 1063.92   164.3 1047.52   228.0 1030.41   244.1 1023.88
   278.1 1007.33   294.3 1000.48   310.6  995.56   383.1  983.35   452.6  976.13
   487.3  966.49   523.1  953.62   530.4  952.92   538.1  954.77   547.3  960.10
   559.6  969.43   572.8  976.49   658.6  997.38   678.4 1003.53   717.0 1017.95
   745.8 1030.50   834.8 1072.30   878.1 1089.60   975.4 1133.44  1048.1 1164.04
#Mann= 3 , 0 , 0
       0     0.1       0   523.1   0.045       0   538.1     0.1       0
Bank Sta=   523.1,   538.1
Exp/Cntr=0.3,0.1

Type RM Length L Ch R = 1 ,907.2,286.196,281.959,280.259
XS GIS Cut Line= 3
     1742896.438      339997.706     1742588.754      339560.266
     1742290.953      339143.637
#Sta/Elev= 30
       0 1187.19    21.5 1176.25    55.6 1160.82    72.6 1155.18    97.9 1148.84
   123.8 1141.22   157.9 1129.03   319.8 1059.98   370.9 1034.55   388.2 1024.44
   464.6  973.70   490.2  956.07   511.4  940.03   518.2  935.95   524.3  934.10
   533.2  935.38   541.3  939.54   552.5  948.51   562.5  954.18   566.9  955.73
   577.1  957.38   626.4  962.33   650.1  966.19   693.9  975.38   779.6  996.45
   796.6 1001.65   881.7 1035.53   927.4 1052.12   981.3 1067.82  1046.9 1081.91
#Mann= 3 , 0 , 0
       0     0.1       0   518.2   0.045       0   533.2     0.1       0
Bank Sta=   518.2,   533.2
Exp/Cntr=0.3,0.1

Type RM Length L Ch R = 1 ,625.2,306.946,318.853,325.57
XS GIS Cut Line= 3
     1743119.745      339703.702     1742752.887      339346.430
     1742435.203      338962.281
#Sta/Elev= 30
       0 1127.73    88.7 1095.63   237.9 1043.81   399.4  984.21   407.8  980.74
   416.2  976.48   466.6  946.23   500.1  927.06   504.6  925.70   508.5  924.45
   517.0  924.29   519.6  924.71   533.8  927.32   543.6  930.03   559.1  937.86
   587.4  955.71   601.3  962.60   618.1  967.79   664.4  977.63   685.6  983.82
   702.5  990.51   719.3  997.91   741.4 1010.70   753.1 1016.78   769.9 1025.12
   785.8 1031.72   837.4 1050.34   941.7 1085.76   963.9 1094.11  1010.6 1113.16
#Mann= 3 , 0 , 0
       0     0.1       0   504.6   0.045       0   519.6     0.1       0
Bank Sta=   504.6,   519.6
Exp/Cntr=0.3,0.1

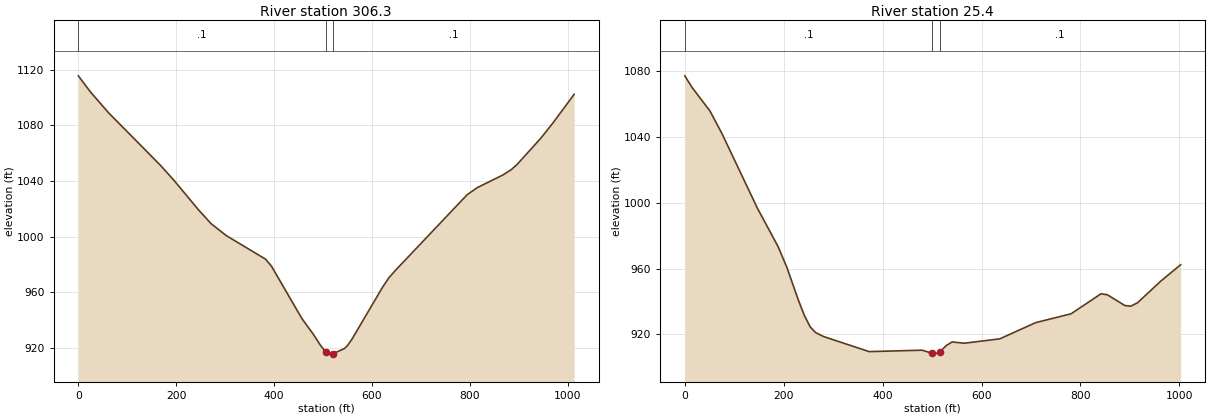
Type RM Length L Ch R = 1 ,306.3,272.452,280.976,293.278
XS GIS Cut Line= 3
     1743153.913      339668.166     1743013.777      339172.546
     1742816.894      338715.191
#Sta/Elev= 30
       0 1115.67    24.5 1104.22    61.5 1089.22   167.9 1051.34   195.0 1040.74
   246.6 1018.96   271.3 1009.44   302.5 1000.82   382.3  984.00   394.6  978.94
   456.3  941.53   481.0  929.55   494.9  921.95   505.9  917.02   514.2  915.72
   520.9  916.07   544.0  919.80   550.3  922.07   559.4  926.66   621.6  963.81
   634.5  970.60   647.4  975.71   794.3 1030.23   815.5 1035.42   867.2 1044.40
   884.7 1048.32   895.4 1051.62   944.7 1070.77   970.6 1082.25  1013.0 1102.41
#Mann= 3 , 0 , 0
       0     0.1       0   505.9   0.045       0   520.9     0.1       0
Bank Sta=   505.9,   520.9
Exp/Cntr=0.3,0.1

Type RM Length L Ch R = 1 ,25.4,23.768,25.369,25.947
XS GIS Cut Line= 3
     1743230.007      339624.136     1743281.803      339111.697
     1743362.968      338631.065
#Sta/Elev= 30
       0 1077.34    15.2 1070.06    51.0 1055.89    74.9 1042.32   146.5  996.92
   188.6  973.34   206.2  960.84   230.0  940.45   242.0  931.26   253.6  924.43
   264.4  921.00   280.8  918.55   372.8  909.39   480.0  910.26   500.4  908.33
   504.5  907.86   515.4  909.06   528.5  913.07   540.5  915.27   565.3  914.51
   636.9  917.17   709.5  927.05   781.0  932.41   841.5  944.61   854.4  944.01
   889.7  937.46   901.8  937.07   915.5  939.16   962.0  952.23  1002.5  962.29
#Mann= 3 , 0 , 0
       0     0.1       0   500.4   0.045       0   515.4     0.1       0
Bank Sta=   500.4,   515.4
Exp/Cntr=0.3,0.1